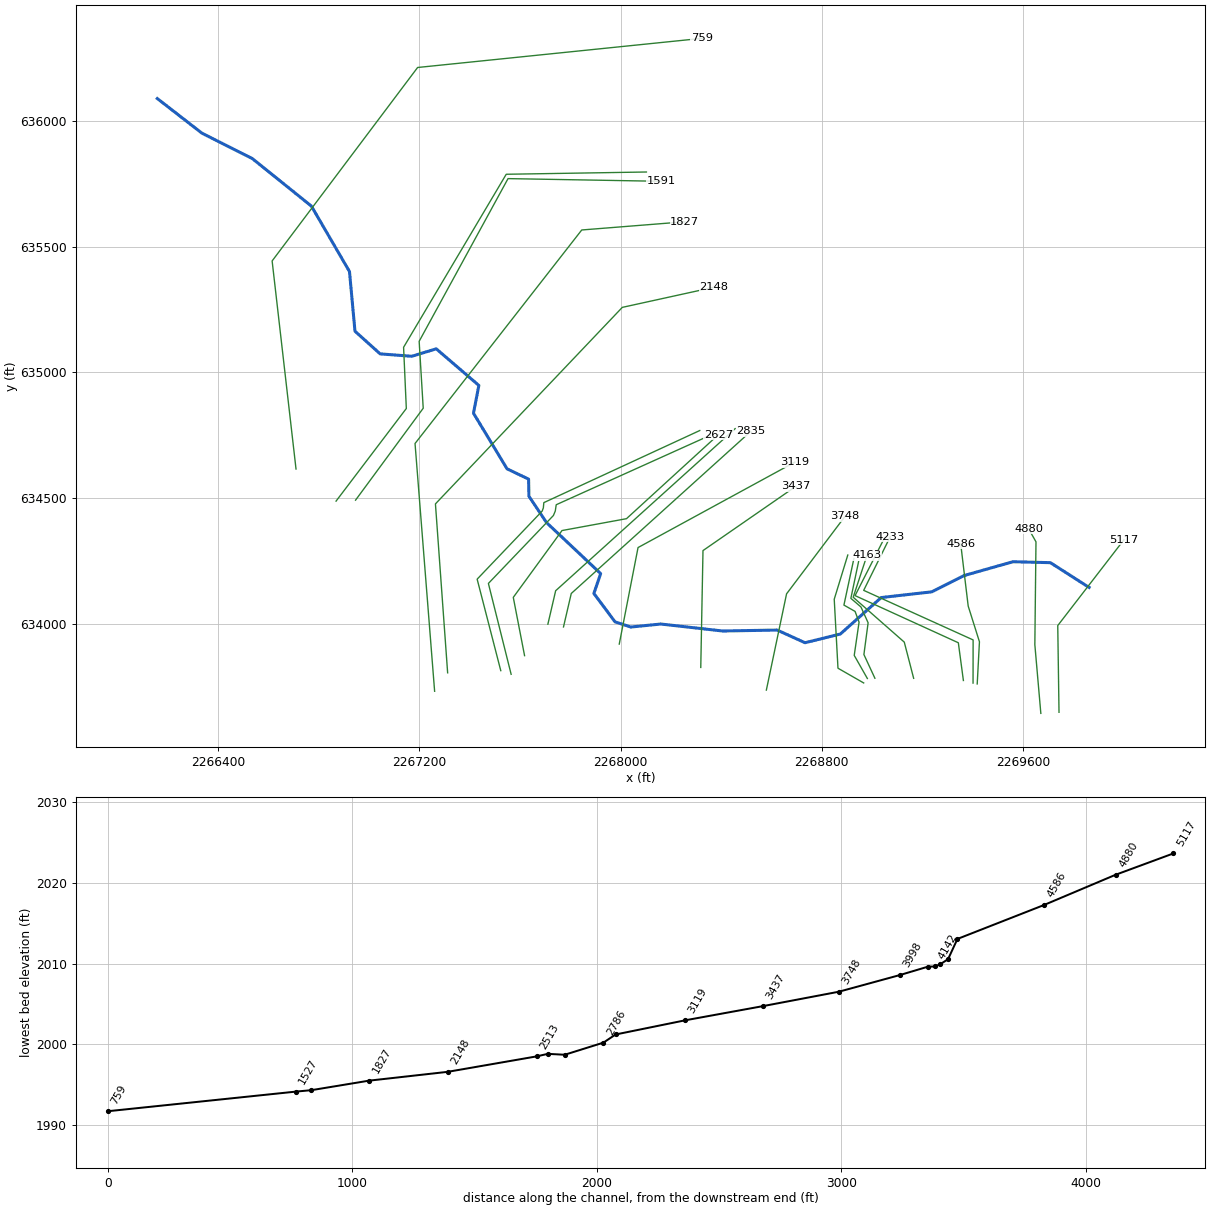
--- JONESRN.prj (project) ---

Proj Title=JONESRN
Current Plan=p01
Default Exp/Contr=0,0
English Units
Geom File=g01
Flow File=f01
Plan File=p01
BEGIN DESCRIPTION:
----------MODEL BY WOOD PLC 2022----------
AFH study
Randolph County, WV
HEC-RAS Version: RAS 6.2
Vertical Datum: NAVD88
Projection: NAD 1983 StatePlane West Virginia S FIPS 4702 (US Feet)
Terrain: 1-meter LIDAR (FEMA Region III 3DEP collected 2016-2018)
Land Use: 2019 NLCD
Hydrologic Method:
WV SIR2010-5033 regression equations
Additional Model Notes:
Backwater from main stem dominates up to ~ RS 3000; irrigation channels on ROB to be mapped by Mapping based on backwater
END DESCRIPTION:
DSS File=dss
DSS Export Rating Curves= 0
DSS Export Rating Curve Sorted= 0
DSS Export Volume Flow Curves= 0
DXF OffsetX= 0
DXF OffsetY= 0
DXF ScaleX= 0
DXF ScaleY= 0

--- JONESRN.p01 (plan) ---

Plan Title=Floodplain
Program Version=6.20
Short Identifier=Floodplain
Geom File=g01
Flow File=f01
Subcritical Flow
K Sum by GR= 0
Std Step Tol= 0.01
Critical Tol= 0.01
Num of Std Step Trials= 20
Max Error Tol= 0.3
Flow Tol Ratio= 0.001
Split Flow NTrial= 30
Split Flow Tol= 0.02
Split Flow Ratio= 0.02
Log Output Level= 0
Friction Slope Method= 1
Unsteady Friction Slope Method= 2
Unsteady Bridges Friction Slope Method= 1
Parabolic Critical Depth
Global Vel Dist= 0 , 0 , 0
Global Log Level= 0
CheckData=True
Encroach Param=-1 ,0,0, 0
Computation Interval=0.1SEC
Output Interval=1SEC
Instantaneous Interval=Max Profile
Mapping Interval=1HOUR
Computation Time Step Use Courant=        0
Computation Time Step Use Time Series=    0
Computation Time Step Count To Double=0
Computation Time Step Max Doubling=0
Computation Time Step Max Halving=0
Computation Time Step Residence Courant=0
Run HTab= 0
Run UNet= 0
Run Sediment= 0
Run PostProcess= 0
Run WQNet= 0
Run RASMapper=-1
UNET Theta= 0
UNET Theta Warmup= 0
UNET ZTol= 0
UNET ZSATol= 0
UNET MxIter= 0
UNET Max Iter WO Improvement= 0
UNET MaxInSteps= 0
UNET DtIC= 0
UNET DtMin= 0
UNET MaxCRTS= 0
UNET WFStab= 0
UNET SFStab= 0
UNET WFX= 1
UNET SFX= 1
UNET Gravity=32.174
UNET 1D Methodology=Finite Difference
UNET DSS MLevel= 1
UNET Pardiso=0
UNET DZMax Abort= 0
UNET Use Existing IB Tables= 0
UNET Froude Reduction=False
UNET Froude Limit= 0
UNET Froude Power= 0
UNET D1 Cores= 0
UNET WindReference=Eulerian
UNET WindDragFormulation=Hsu (1988)
UNET D2 Coriolis=0
UNET D2 Cores= 0
UNET D2 Theta= 1
UNET D2 Theta Warmup= 1
UNET D2 Z Tol= 0.01
UNET D2 Volume Tol= 0.01
UNET D2 Max Iterations= 20
UNET D2 Equation= 0
UNET D2 RampUpFraction=0.1
UNET D2 TimeSlices= 1
UNET D2 Turbulence Formulation=Non-Conservative (original)
UNET D2 Eddy Viscosity=0.3
UNET D2 Transverse Eddy Viscosity=0.1
UNET D2 Smagorinsky Mixing=0
UNET D2 BCVolumeCheck=0
UNET D2 Cores=0
UNET D2 SolverType=PARDISO (Direct)
UNET D2 Minimum Iterations= 2147483647
UNET D2 Maximum Iterations= 2147483647
UNET D2 Restart Number= 10
UNET D2 Relaxation Coeff=1.3
UNET D2 SOR Precondition Iterations= 10
UNET D2 ILUT Maximum Fill= 8
UNET D2 ILUT Tolerance=1E-08
UNET D1D2 MaxIter= 0
UNET D1D2 ZTol=0.01
UNET D1D2 QTol=0.1
UNET D1D2 MinQTol=1
DSS File=dss
Write IC File= 0
Write IC File at Fixed DateTime=0
Write IC File at Sim End=0
Echo Input=False
Echo Parameters=False
Echo Output=False
Write Detailed= 0
HDF Write Warmup=0
HDF Write Time Slices=0
HDF Flush=0
HDF Compression= 1
HDF Chunk Size= 1
HDF Spatial Parts= 1
HDF Use Max Rows=0
HDF Fixed Rows= 1
Calibration Method= 0
Calibration Iterations= 20
Calibration Max Change=0.05
Calibration Tolerance=0.2
Calibration Maximum=1.5
Calibration Minimum=0.5
Calibration Optimization Method= 1
WQ AD Non Conservative
WQ ULTIMATE=-1
WQ Max Comp Step=1HOUR
WQ Output Interval=15MIN
WQ Output Selected Increments= 0
WQ Output face flow=0
WQ Output face velocity=0
WQ Output face area=0
WQ Output face dispersion=0
WQ Output cell volume=0
WQ Output cell surface area=0
WQ Output cell continuity=0
WQ Output cumulative cell continuity=0
WQ Output face conc=0
WQ Output face dconc_dx=0
WQ Output face courant=0
WQ Output face peclet=0
WQ Output face adv mass=0
WQ Output face disp mass=0
WQ Output cell mass=0
WQ Output cell source sink temp=0
WQ Output nsm pathways=0
WQ Output nsm derived pathways=0
WQ Create Restart=0
WQ Fixed Restart=0
WQ System Summary=0
WQ Write To DSS=0
Sorting and Armoring Iterations= 10
XS Update Threshold= 0.02
Bed Roughness Predictor= 0
Hydraulics Update Threshold= 0.02
Energy Slope Method= 1
Volume Change Method= 1
Sediment Retention Method= 0
Sediment TS Multiplier= 1
Warm Up Method= 0
XS Weighting Method= 0
Number of US Weighted Cross Sections= 1
Number of DS Weighted Cross Sections= 1
Upstream XS Weight=0
Main XS Weight=1
Downstream XS Weight=0
Number of DS XS's Weighted with US Boundary= 1
Upstream Boundary Weight= 1
Weight of XSs Associated with US Boundary= 0
Number of US XS's Weighted with DS Boundary= 1
Downstream Boundary Weight= 0.5
Weight of XSs Associated with DS Boundary= 0.5
Percentile Method= 0
Sediment Output Level= 3
Mass or Volume Output= 0
Output Increment Type= 1
Profile and TS Output Increment= 1
Transport Output Increment 1
XS Output Flag= 0
XS Output Increment= 10
Read HDF5 Sediment Hotstart= 0
Sediment Hotstart Type= 0
Write Gradation File= 0
Read Gradation Hotstart= 0
Write HDF5 File= 1
Write Binary Output= 1
Write DSS Sediment File= 0
DSS Sediment Output Type= 1
SV Curve= 0
Specific Gage Flag= 0
Subcell Erosion Methods= 0
Subcell Deposition Methods= 0
Advection Scheme= 1
Matrix Solver= 0
Implicit Weighting Factor= 1
Maximum Outer Loop Convergence Iterations= 5
Convergence Maximum Absolute= 0.001
Convergence RMSE= 0.0001
Grain Fractions Max Abs Error= 0.001
Max Subgrid Regions= 1
Max Subgrid Length Scale= 3.402823E+38
Initial Layer Thickness= 3.402823E+38
Min Layer Thickness= 3.402823E+38
Max Layer Thickness= 3.402823E+38
Number of Layers= 5

--- JONESRN.f01 (steady flow) ---

Flow Title=Flow
Program Version=6.20
Number of Profiles= 1
Profile Names=P100yr
River Rch & RM=JONESRN,Main            ,5117
     371
Boundary for River Rch & Prof#=JONESRN,Main            , 1
Up Type= 0
Dn Type= 3
Dn Slope=0.00351
DSS Import GetInterval= 0
DSS Import GetPeak= 0
DSS Import FillOption= 0

--- JONESRN.g01 (geometry) ---

Geom Title=Geometry
Program Version=6.20

River Reach=JONESRN         ,Main
Reach XY= 30
2269863.47778243634145.710254127     2269709.605      634244.128
     2269560.928      634247.908     2269366.892      634193.099
     2269237.745       634128.21      2269036.78      634105.531
     2268874.244      633960.634     2268733.757      633925.985
      2268622.88      633976.384     2268406.165      633972.604
      2268160.47      634000.3242268040.98098072633988.435740377
2267978.12389303634008.928873077     2267893.986      634121.911
     2267921.076      634200.659     2267705.621      634403.514
     2267635.692      634508.092     2267634.432       634576.13
     2267548.755      634617.079     2267415.197      634838.204
     2267436.617      634948.452     2267267.151      635093.978
     2267170.133      635064.369     2267044.136      635073.819
     2266943.968      635163.9072266922.06485518635401.193034549
     2266770.622      635661.141     2266535.965      635849.835
     2266335.176      635951.036     2266157.772      636088.523

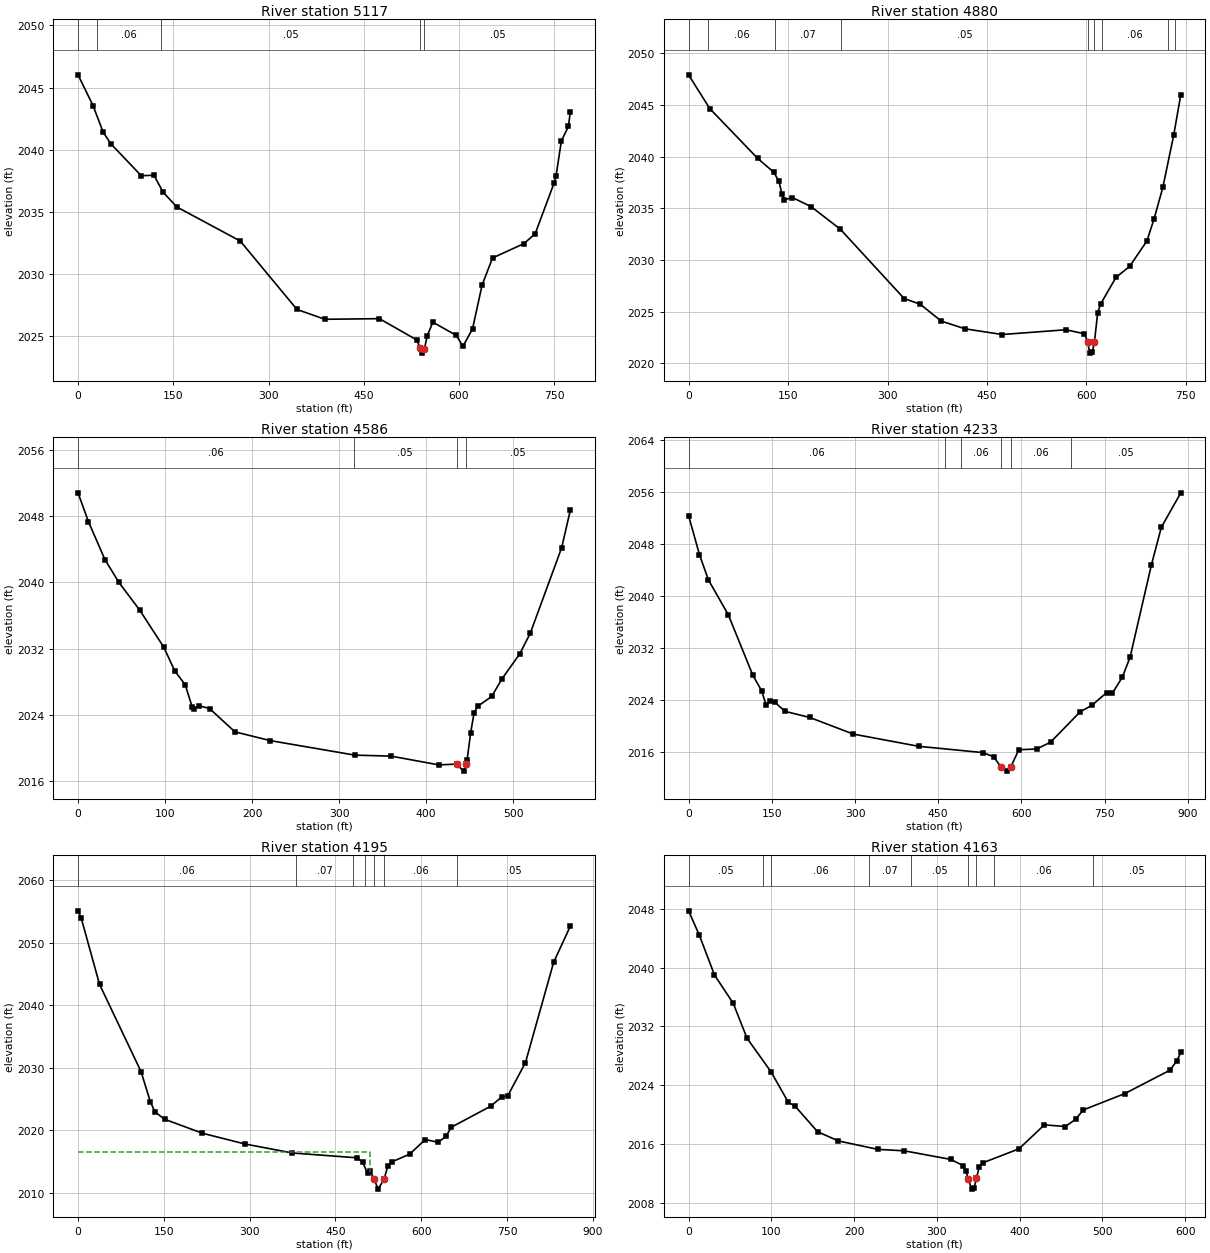
Type RM Length L Ch R = 1 ,5117    ,232.7,236.8,238.8
XS GIS Cut Line= 3
 2269743.8317312633649.6304947062269738.81976623633994.203086866
2270001.94792751634335.016705293
#Sta/Elev= 30
       0 2046.02    23.6 2043.55    39.6 2041.41    51.6 2040.48    99.6 2037.91
   119.6 2037.95   133.9 2036.59   155.6  2035.4   255.5 2032.66   344.8 2027.16
   388.8 2026.37   474.7 2026.42   533.1 2024.72   538.8 2024.07   541.6 2023.65
   545.5 2023.98   549.7 2024.99   558.7 2026.14     596 2025.07   606.1 2024.19
   621.3  2025.6   636.4 2029.13   652.8  2031.3   702.1 2032.45   719.9 2033.24
   749.8 2037.33   752.7 2037.85   761.2  2040.7   772.3 2041.87   775.2 2043.01
#Mann= 5 ,-1,0
       0     .08       0      30     .06       0     130     .05       0
   538.8    .045       0   545.5     .05       0
Bank Sta=538.8,545.5
XS Rating Curve= 0 ,0
Exp/Cntr(USF)=0,0
Exp/Cntr=0.3,0.1

Type RM Length L Ch R = 1 ,4880    ,291.7,293.7,293.1
XS GIS Cut Line= 4
2269671.53483521633645.257457013 2269647.7120093633918.239015113
2269652.22965789634327.0445934062269622.84224025634378.778102023
#Sta/Elev= 30
       0 2047.92      32 2044.65   104.3 2039.83   128.4  2038.5   136.4 2037.61
   140.5 2036.44   144.5 2035.83   156.5 2036.05   184.6 2035.18   228.8 2032.99
   325.1 2026.28   349.3 2025.73     381  2024.1     417 2023.35     473  2022.8
     569 2023.26     597 2022.87   601.8 2022.12     605    2021     609 2021.13
   612.12022.116     617 2024.92   621.6 2025.78   644.6 2028.33     665 2029.38
   691.1 2031.84   702.1 2034.01   715.4 2037.08   731.6 2042.09   742.3    2046
#Mann= 9 ,-1,0
       0     .08       0      30     .06       0     130     .07       0
     230     .05       0   601.8    .045       0   612.1     .05       0
  624.02     .06       0  722.85     .05       0  732.85      .1       0
Bank Sta=601.8,612.1
XS Rating Curve= 0 ,0
Exp/Cntr(USF)=0,0
Exp/Cntr=0.3,0.1

Type RM Length L Ch R = 1 ,4586    ,341.7,352.8,357.6
XS GIS Cut Line= 4
2269418.53335075 633762.285780232269427.38155077633929.861120258
2269382.63218858634071.7042373892269352.90384439634318.849555352
#Sta/Elev= 30
       0  2050.8    11.9 2047.34    30.9 2042.75      47 2039.99      71 2036.64
    98.6 2032.17     111 2029.35   123.1 2027.66   131.1    2025   133.7 2024.77
   139.1 2025.12   151.1 2024.79   180.2 2021.98   220.8 2020.92     318 2019.17
   359.6 2019.05   414.7 2017.99   434.9 2018.09   442.9 2017.24  445.65 2018.09
     447 2018.59     451 2021.81     455 2024.27     459 2025.05   475.2 2026.24
   487.2 2028.39   507.4 2031.37   519.5 2033.85   555.7  2044.2   565.5 2048.67
#Mann= 4 ,-1,0
       0     .06       0  316.54     .05       0   434.9    .045       0
  445.65     .05       0
Bank Sta=434.9,445.65
XS Rating Curve= 0 ,0
Exp/Cntr(USF)=0,0
Exp/Cntr=0.3,0.1

Type RM Length L Ch R = 1 ,4233    ,41.1,38.3,40.6
XS GIS Cut Line= 4
2269401.95774982633765.6004429762269402.23954426633937.143100422
2268967.06006682634134.1400422142269072.74905213634347.545792595
#Sta/Elev= 30
       0 2052.33    19.6 2046.35    35.6 2042.48    71.6 2037.09   115.6 2027.84
   131.6 2025.42   139.6 2023.27   147.6  2023.8   155.6 2023.64   173.8 2022.24
   218.5  2021.3   297.1 2018.74   415.3 2016.86   530.5  2015.9   549.9 2015.26
     563 2013.71   573.4 2013.05   581.2 2013.74   595.3 2016.34   627.5 2016.45
   652.6  2017.5   706.2 2022.19     727 2023.16   753.8 2025.13   764.2 2025.06
   782.1 2027.51     796 2030.58   834.4 2044.75   852.3 2050.55   887.4 2055.84
#Mann= 6 ,-1,0
       0     .06       0  461.54     .07       0  491.54     .06       0
     563    .045       0   581.2     .06       0  689.23     .05       0
Bank Sta=563,581.2
XS Rating Curve= 0 ,0
Exp/Cntr(USF)=0,0
Exp/Cntr=0.3,0.1

Type RM Length L Ch R = 1 ,4195    ,34.5,32.3,29.8
XS GIS Cut Line= 4
2269363.57895928633775.8785443032269343.42917715633925.854537585
2268932.76689891634113.2295739722269049.90469039634342.948579596
#Sta/Elev= 30
       0  2055.1     5.3 2054.03    37.6 2043.33   110.3 2029.33   126.4 2024.53
   134.5 2022.91   151.3 2021.73   217.1  2019.5   291.2 2017.78   374.7 2016.33
     487 2015.56   497.5  2014.9   506.2 2013.06     511 2013.37   517.7 2012.17
   524.6 2010.54   535.1 2012.13   541.8 2014.27   548.8 2014.91   579.8 2016.14
   607.1 2018.48   629.6 2018.04   643.1 2018.97   652.8 2020.46   721.2  2023.8
   741.8 2025.37   750.9 2025.41   782.3  2030.8   831.6 2046.87   860.6 2052.62
#Mann= 7 ,-1,0
       0     .06       0  381.32     .07       0  481.32     .05       0
  501.32     .06       0   517.7    .045       0   535.1     .06       0
  662.71     .05       0
#XS Ineff= 2 , 0
          511.19 2016.51
Permanent Ineff=
       F       F
Bank Sta=517.7,535.1
XS Rating Curve= 0 ,0
Exp/Cntr(USF)=0,0
Exp/Cntr=0.3,0.1

Type RM Length L Ch R = 1 ,4163    ,23.3,20.3,17.7
XS GIS Cut Line= 4
2269165.71898394633784.6135975092269128.48472281633928.344035809
2268925.31174186634106.7745581362268980.33384922634273.678367509
#Sta/Elev= 30
       0  2047.7      13 2044.39    31.3 2038.98      54 2035.13    70.6  2030.4
    99.8 2025.81   120.4 2021.71   128.7 2021.17   155.8 2017.71   180.8 2016.46
   228.5 2015.31   260.7 2015.11   316.5 2013.95   331.6 2013.11   335.2 2012.33
  337.71  2011.3     342 2009.91   344.9 2010.06   347.7 2011.36   351.2 2012.98
   355.8  2013.5   399.1 2015.38   429.8 2018.64   455.1 2018.41   467.4 2019.38
   476.9 2020.67   526.7 2022.87   581.5 2026.06   589.9 2027.34   594.6 2028.47
#Mann= 9 ,-1,0
       0     .05       0      90     .07       0     100     .06       0
  218.48     .07       0  268.48     .05       0  337.71    .045       0
   347.7     .05       0  368.48     .06       0  488.88     .05       0
Bank Sta=337.71,347.7
XS Rating Curve= 0 ,0
Exp/Cntr(USF)=0,0
Exp/Cntr=0.3,0.1

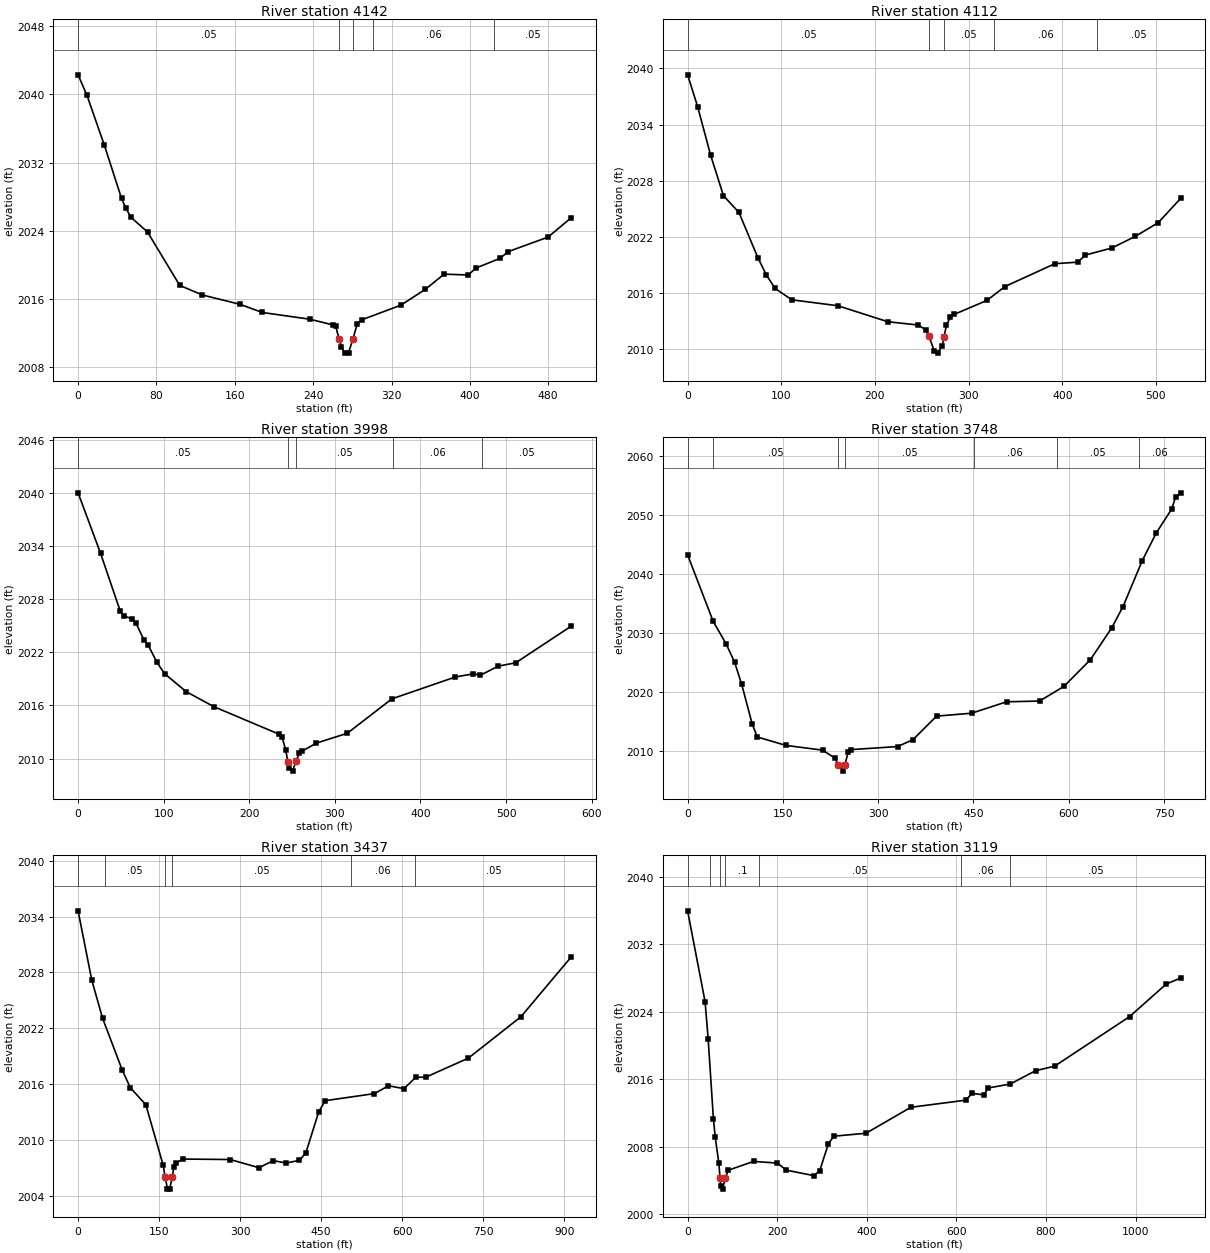
Type RM Length L Ch R = 1 ,4142    ,30.5,30,29.5
XS GIS Cut Line= 6
2269011.60330584633784.8967152152268967.89648555633879.032329656
2268984.62486015634005.3315578412268956.18662334634068.062962568
2268916.03852431634102.3561304862268946.71399665634248.253195454
#Sta/Elev= 30
       0  2042.3     9.1 2039.89    26.8 2034.05    44.4 2027.79    48.8 2026.65
      54 2025.58    70.9 2023.85   103.8 2017.59     127 2016.46     165 2015.38
   188.1 2014.41   236.7 2013.62   259.9 2012.96     263  2012.8   266.42011.343
   268.9 2010.41   272.3 2009.64   276.2 2009.71   280.5 2011.26     285 2013.06
   289.4 2013.54   329.4 2015.26   354.4 2017.11   373.7 2018.91   398.2 2018.81
   406.4 2019.63   430.9 2020.77   439.1 2021.55   479.9 2023.26   503.5 2025.53
#Mann= 5 ,-1,0
       0     .05       0   266.4    .045       0   280.5     .05       0
  301.34     .06       0  424.42     .05       0
Bank Sta=266.4,280.5
XS Rating Curve= 0 ,0
Exp/Cntr(USF)=0,0
Exp/Cntr=0.3,0.1

Type RM Length L Ch R = 1 ,4112    ,115,113.9,115.2
XS GIS Cut Line= 6
2268981.60721662633783.8942920532268929.42122399633875.686654737
2268948.65885477 634007.840814032268932.76689891634050.498169244
2268888.43670623634075.5907311352268928.16596986634260.716474183
#Sta/Elev= 30
       0 2039.32    10.7 2035.93    24.5 2030.77    38.3 2026.41    54.8 2024.63
    75.1 2019.78    84.1 2017.95    93.5 2016.51   111.3  2015.3   160.4 2014.67
   213.8 2012.96   246.3 2012.61   254.9 2012.05   257.82011.393   263.4 2009.81
   266.9 2009.61   271.9 2010.41   273.82011.365   276.4 2012.63   280.5 2013.42
   284.7 2013.75   319.6 2015.24   338.8 2016.72   392.2 2019.16   416.5 2019.32
   424.7 2020.08   452.8 2020.83   477.9 2022.07   502.5 2023.54   526.5 2026.14
#Mann= 5 ,-1,0
       0     .05       0   257.8    .045       0   273.8     .05       0
  327.26     .06       0  437.18     .05       0
Bank Sta=257.8,273.8
XS Rating Curve= 0 ,0
Exp/Cntr(USF)=0,0
Exp/Cntr=0.3,0.1

Type RM Length L Ch R = 1 ,3998    ,250,250,247.6
XS GIS Cut Line= 4
2268967.01613845633766.177811582 2268864.7871826633824.727122661
2268849.91751629634098.8865951742268903.82005665634274.534528411
#Sta/Elev= 30
       0 2040.04    26.3 2033.19    49.4 2026.63    54.1  2026.1    62.9  2025.8
    67.8 2025.27      77 2023.41    81.6 2022.87    92.2 2020.87     101  2019.6
   126.1 2017.58   158.3 2015.88   234.4 2012.77   238.4 2012.39   242.4 2011.02
   245.22009.605   246.4 2008.97   250.5 2008.58   254.5 2009.67   258.5 2010.62
   261.6 2010.84   278.5 2011.75   314.5 2012.86   366.6 2016.75   440.7 2019.22
   461.7 2019.58   470.1 2019.43     491 2020.45   511.3 2020.83   576.1 2024.97
#Mann= 5 ,-1,0
       0     .05       0   245.2    .045       0   254.5     .05       0
  367.81     .06       0  472.37     .05       0
Bank Sta=245.2,254.5
XS Rating Curve= 0 ,0
Exp/Cntr(USF)=0,0
Exp/Cntr=0.3,0.1

Type RM Length L Ch R = 1 ,3748    ,310.2,311.4,312.1
XS GIS Cut Line= 3
2268579.95904906633737.791803892 2268660.3292709634120.261740488
2268892.67009901 634427.92762808
#Sta/Elev= 30
       0 2043.23    40.2 2031.95    60.5 2028.15      74 2025.01    85.2 2021.23
   101.6 2014.54   109.7 2012.31   154.7 2010.88   212.5 2010.07   232.4 2008.69
  237.37 2007.49   244.6 2006.51   247.3 2007.48   252.8 2009.71   256.9 2010.16
   330.7 2010.68     355 2011.87     392 2015.85   447.1 2016.34   502.2 2018.28
   554.1 2018.41   592.5  2020.9   634.1 2025.42   667.7 2030.83   685.5 2034.45
   715.8 2042.25   737.8 2046.94   762.3 2051.03   768.3 2053.08   776.4 2053.76
#Mann= 7 ,-1,0
       0      .1       0      40     .05       0  237.37    .045       0
   247.3     .05       0  450.82     .06       0  580.82     .05       0
  710.82     .06       0
Bank Sta=237.37,247.3
XS Rating Curve= 0 ,0
Exp/Cntr(USF)=0,0
Exp/Cntr=0.3,0.1

Type RM Length L Ch R = 1 ,3437    ,318.3,318.3,316.3
XS GIS Cut Line= 3
2268319.12621065 633827.796216842268327.97186155634292.195502827
2268696.83667493634547.200879775
#Sta/Elev= 30
       0 2034.61    25.4 2027.16    45.4 2023.07    81.4 2017.56    96.6 2015.62
   125.4 2013.79   157.4 2007.31   161.4 2005.97   165.4 2004.77   169.4 2004.72
  174.28 2005.99   177.4 2007.07   181.4 2007.49   193.4 2007.95   281.8  2007.9
   334.8 2007.02   361.4 2007.78   385.5 2007.52   409.5 2007.81   421.5 2008.59
   445.5 2013.02   457.5 2014.22   548.7 2014.98   574.6 2015.82   603.3 2015.51
   625.2 2016.74   643.6 2016.74   722.5 2018.79   819.7 2023.23   912.9 2029.66
#Mann= 6 ,-1,0
       0      .1       0      50     .05       0   161.4    .045       0
  174.28     .05       0  504.48     .06       0  624.48     .05       0
Bank Sta=161.4,174.28
XS Rating Curve= 0 ,0
Exp/Cntr(USF)=0,0
Exp/Cntr=0.3,0.1

Type RM Length L Ch R = 1 ,3119    ,282.6,283.3,279.6
XS GIS Cut Line= 3
2267994.93117943 633920.620922792268069.69256503634304.192549071
2268693.36589015634643.795489804
#Sta/Elev= 30
       0 2035.98    39.1 2025.18    45.9 2020.78    57.6 2011.31    61.7 2009.11
    69.7 2006.05    72.52004.244    73.9 2003.37      78 2002.96    84.22004.236
    90.2 2005.19   147.3 2006.25   200.3 2006.05   220.6 2005.21   281.8 2004.56
   294.8 2005.13   314.4 2008.36   326.6 2009.24   398.2 2009.59   498.4 2012.67
   620.4 2013.51   635.4 2014.32   661.7 2014.14   670.5 2014.95   720.7 2015.44
   776.7 2017.01   819.4 2017.55   986.7 2023.43  1068.6  2027.3  1100.9 2028.01
#Mann= 7 ,-1,0
       0     .05       0      50      .1       0    72.5    .045       0
    84.2      .1       0     160     .05       0  610.79     .06       0
  720.79     .05       0
Bank Sta=72.5,84.2
XS Rating Curve= 0 ,0
Exp/Cntr(USF)=0,0
Exp/Cntr=0.3,0.1

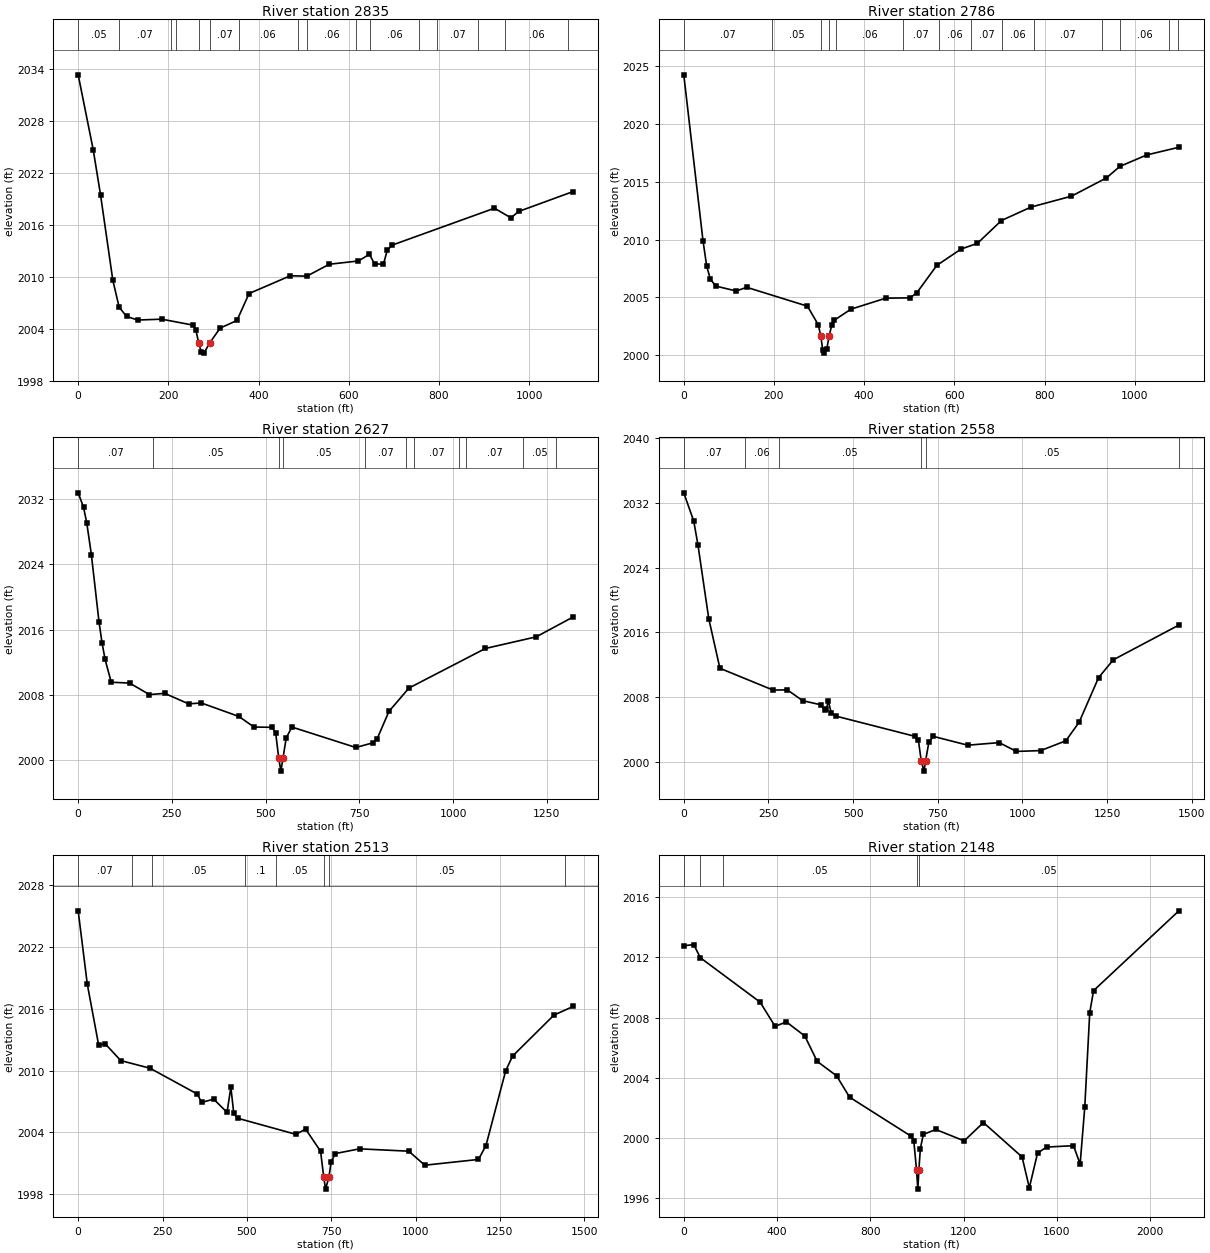
Type RM Length L Ch R = 1 ,2835    ,49.8,49.7,50.5
XS GIS Cut Line= 3
2267773.17814869633988.7509159052267804.10111095 634121.69162678
2268517.93238141 634765.83838626
#Sta/Elev= 30
       0 2033.34    33.3 2024.71    49.7 2019.45    76.8 2009.64    90.8 2006.52
   107.2 2005.45   131.9 2005.03   185.1 2005.13   255.1 2004.44   261.1 2003.87
   267.1 2002.43   273.1 2001.29     279 2001.21   291.9  2002.4   314.8  2004.1
   352.1 2004.98     379 2008.09   470.4 2010.14   507.2  2010.1   556.8 2011.47
   621.5 2011.85     646 2012.62   657.3  2011.5   677.1 2011.49   685.6 2013.12
   696.9 2013.69   923.2 2017.94   959.7 2016.83   977.1 2017.57    1098 2019.87
#Mann= 16 ,-1,0
       0     .05       0      90     .07       0  206.49     .05       0
  216.49     .07       0   267.1    .045       0   291.9     .07       0
  356.49     .06       0  486.49     .05       0  506.49     .06       0
  616.49     .05       0  646.49     .06       0  756.49     .05       0
  796.49     .07       0  886.49     .05       0  946.49     .06       0
 1086.49     .07       0
Bank Sta=267.1,291.9
XS Rating Curve= 0 ,0
Exp/Cntr(USF)=0,0
Exp/Cntr=0.3,0.1

Type RM Length L Ch R = 1 ,2786    ,156.2,158.2,159.7
XS GIS Cut Line= 3
2267711.10840233633999.6977860262267742.03136459634132.638496901
2268455.86263505634776.785256381
#Sta/Elev= 30
       0 2024.21    42.6  2009.9    50.8 2007.71      59 2006.57    71.3 2005.98
   116.5 2005.56   139.4 2005.88   274.3 2004.25   298.5 2002.63   303.92001.647
   308.3 2000.46   311.8  2000.2   317.2 2000.57   322.22001.639   328.1 2002.62
   333.8 2003.04   370.6 2003.99   447.8 2004.94   501.5 2004.97   516.5 2005.39
   561.2 2007.77     615 2009.18   651.2 2009.67   704.5 2011.64     770  2012.8
   859.7 2013.74   937.1 2015.31   967.2 2016.31  1026.9  2017.3    1098 2017.96
#Mann= 14 ,-1,0
       0     .07       0  196.49     .05       0   303.9    .045       0
   322.2     .07       0  336.49     .06       0  486.49     .07       0
  566.49     .06       0  636.49     .07       0  706.49     .06       0
  776.49     .07       0  926.49     .05       0  966.49     .06       0
 1076.49     .05       0 1096.49     .07       0
Bank Sta=303.9,322.2
XS Rating Curve= 0 ,0
Exp/Cntr(USF)=0,0
Exp/Cntr=0.3,0.1

Type RM Length L Ch R = 1 ,2627    ,70.2,69.2,68.9
XS GIS Cut Line= 5
 2267618.3894282633874.654911933 2267573.5041716634106.212856692
2267767.26638833634371.8122181542268023.70508363634418.938615729
2268389.10418063634752.742420871
#Sta/Elev= 30
       0 2032.73    14.3 2030.96    22.9 2029.06    35.2 2025.17    55.5 2016.98
    63.7 2014.37    71.8 2012.36    88.1 2009.57     137 2009.47     190 2008.06
   230.7 2008.21   294.3 2006.93   328.8 2007.03   428.8 2005.38   468.9 2004.09
   516.8 2004.06   526.7 2003.36   534.8 2000.31   540.5  1998.7   546.2  2000.3
   554.8 2002.76     570 2004.09   740.4 2001.59   785.2 2002.15   797.4 2002.66
   828.7    2006   882.1 2008.86  1086.1  2013.7  1221.5 2015.12  1320.3 2017.56
#Mann= 11 ,-1,0
       0     .07       0     200     .05       0   534.8    .045       0
   546.2     .05       0  764.63     .07       0  875.37     .06       0
  895.37     .07       0 1015.37     .06       0 1035.37     .07       0
 1185.37     .05       0 1275.37     .06       0
Bank Sta=534.8,546.2
XS Rating Curve= 0 ,0
Exp/Cntr(USF)=0,0
Exp/Cntr=0.3,0.1

Type RM Length L Ch R = 1 ,2558    ,44.6,45.2,45
XS GIS Cut Line= 6
2267564.99827316633800.5424124852267474.53381659634161.604414512
2267733.10407423634431.6168420162267740.53890738634449.274570754
2267744.25632395634474.3671326452268356.75121659634750.404878472
#Sta/Elev= 30
       0 2033.26    29.5 2029.75    41.9  2026.8    73.7  2017.7   106.7 2011.54
   263.9 2008.84   305.8 2008.87   351.2 2007.53   404.9 2007.02   415.9 2006.34
   421.5 2006.45   426.8 2007.54   435.3 2006.06   449.5 2005.62   681.5 2003.13
   692.9 2002.64   701.3 2000.11   709.5 1998.81   714.4 2000.12   723.9 2002.39
   737.2 2003.11   838.8 2002.02   931.8 2002.34   982.4 2001.25  1053.8 2001.35
  1128.4 2002.56  1167.7 2004.86  1225.2 2010.38  1268.7 2012.59  1462.4 2016.89
#Mann= 6 ,-1,0
       0     .07       0     180     .06       0     280     .05       0
   701.3    .045       0   714.4     .05       0 1462.42     .06       0
Bank Sta=701.3,714.4
XS Rating Curve= 0 ,0
Exp/Cntr(USF)=0,0
Exp/Cntr=0.3,0.1

Type RM Length L Ch R = 1 ,2513    ,363.5,364.6,362.8
XS GIS Cut Line= 6
 2267523.7553937633815.0203266092267429.82564154634178.620315971
2267688.49507531634449.2745707542267693.14184603634462.285528772
2267695.00055432634482.731319942 2268315.1492124634769.277673682
#Sta/Elev= 30
       0  2025.5      27 2018.39    60.5 2012.51    80.7 2012.58   126.2 2010.97
   212.9 2010.23   353.4 2007.72   365.7 2006.91   401.6 2007.23   441.2 2005.95
   452.6 2008.39   461.1 2005.85   472.4 2005.38   644.9 2003.82   674.2 2004.32
   718.5 2002.17   727.7 1999.69   733.2  1998.5   743.3 1999.69   749.6 2001.13
   762.1 2001.95     834 2002.41   979.9 2002.18  1027.4 2000.82  1186.5 2001.38
  1208.6 2002.73  1266.9 2009.96  1287.3  2011.4    1410 2015.38  1467.4 2016.23
#Mann= 8 ,-1,0
       0     .07       0     160     .06       0     220     .05       0
  495.54      .1       0  585.54     .05       0   727.7    .045       0
   743.3     .05       0 1444.27     .06       0
Bank Sta=727.7,743.3
XS Rating Curve= 0 ,0
Exp/Cntr(USF)=0,0
Exp/Cntr=0.3,0.1

Type RM Length L Ch R = 1 ,2148    ,317.1,320.9,318.9
XS GIS Cut Line= 4
2267312.45680796633806.4236129422267263.94130849634477.710167283
2268007.06393894635258.679199873 2268370.7702977635338.472309422
#Sta/Elev= 30
       0 2012.78    42.9 2012.85    70.9 2011.98   327.6 2009.02   391.7 2007.41
   439.9 2007.71     519 2006.77   572.2 2005.08   655.4 2004.12     711  2002.7
     976 2000.09   986.7 1999.76   998.1 1997.88  1003.9 1996.58 1008.44 1997.88
  1014.6 1999.28  1027.3 2000.22  1080.9 2000.55  1202.4 1999.79  1285.2 2001.01
  1450.9 1998.72    1482 1996.67  1517.1 1998.97  1555.7 1999.38  1671.4 1999.47
  1699.9 1998.25  1719.7 2002.02  1741.1 2008.33  1757.5 2009.79  2123.4  2015.1
#Mann= 5 ,-1,0
       0     .07       0      70     .06       0     170     .05       0
   998.1    .045       0 1008.44     .05       0
Bank Sta=998.1,1008.44
XS Rating Curve= 0 ,0
Exp/Cntr(USF)=0,0
Exp/Cntr=0.3,0.1

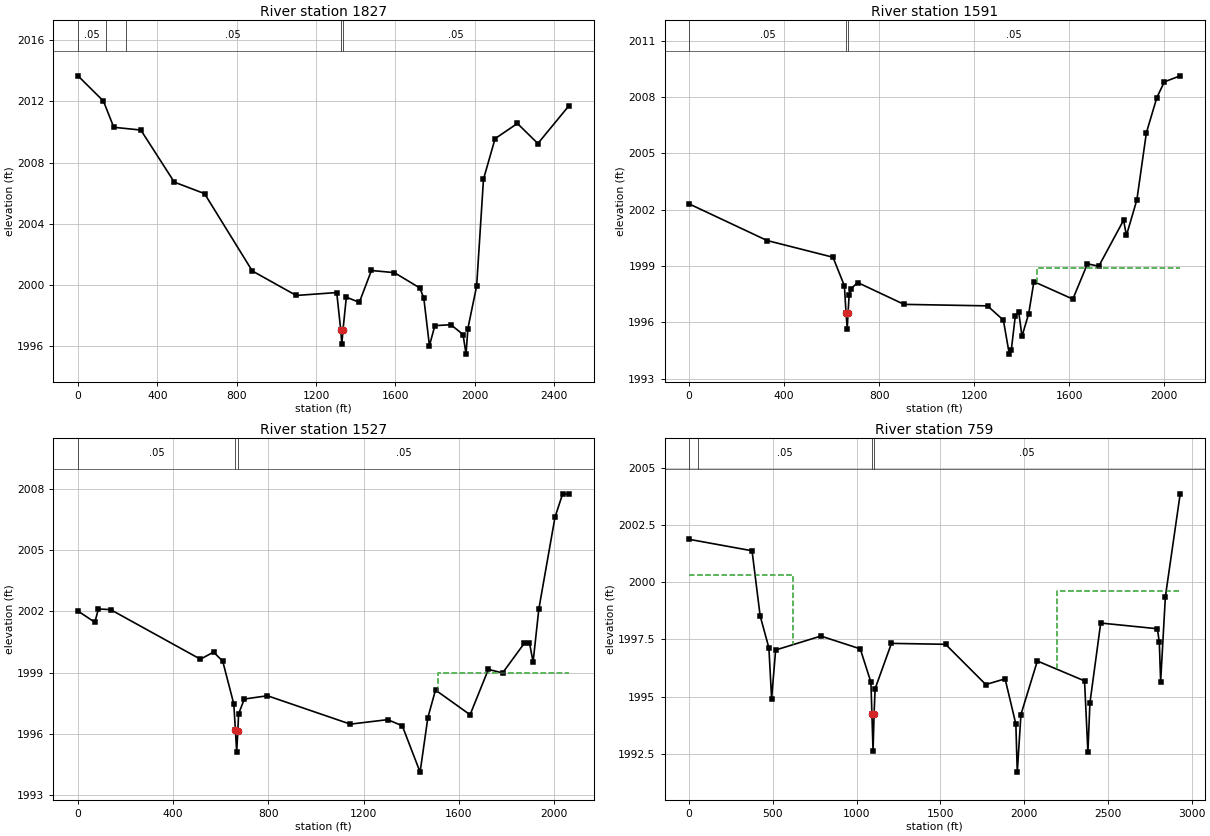
Type RM Length L Ch R = 1 ,1827    ,230.7,236.1,237.8
XS GIS Cut Line= 4
2267260.68188102633733.1317980732267182.81773072634717.692027331
2267845.78913338 635566.248120752268255.50825016635598.801235071
#Sta/Elev= 30
       0 2013.66   128.4 2012.01   180.6  2010.3     317 2010.12   485.6 2006.72
     638 2005.97   878.8 2000.92  1100.3 1999.32  1304.5 1999.51  1324.9 1997.05
  1330.2 1996.15 1335.95 1997.05    1353 1999.21  1418.5 1998.87  1479.4 2000.95
  1595.2 2000.81  1723.4 1999.81  1743.5 1999.15  1771.9 1996.04  1799.2 1997.35
  1880.2 1997.41  1941.3 1996.77  1956.5 1995.49  1965.7 1997.16  2009.9 1999.94
  2044.4 2006.91  2102.9 2009.56  2215.3 2010.55  2318.5 2009.24  2475.5 2011.71
#Mann= 5 ,-1,0
       0     .05       0     140     .06       0     240     .05       0
  1324.9    .045       0 1335.95     .05       0
Bank Sta=1324.9,1335.95
XS Rating Curve= 0 ,0
Exp/Cntr(USF)=0,0
Exp/Cntr=0.3,0.1

Type RM Length L Ch R = 1 ,1591    ,64.2,64,63.9
XS GIS Cut Line= 5
2266946.24486476634492.5899754532267215.36417629634857.823326809
2267199.17599781635123.8177980052267552.63700603635770.363633424
2268162.42093063635759.636839306
#Sta/Elev= 30
       0 2002.31   327.9 2000.36   605.3 1999.47   653.4 1997.95   660.4 1996.49
   665.4 1995.67  668.86 1996.49   673.4 1997.47   681.5  1997.8   709.5 1998.12
   904.6 1996.96  1255.9 1996.88  1322.6 1996.12  1347.6 1994.31    1356 1994.53
  1372.7 1996.33  1387.3 1996.55    1401 1995.26  1429.3 1996.47  1451.1 1998.17
    1615 1997.24  1676.6 1999.12  1724.1 1998.99  1828.6 2001.44  1840.6 2000.63
  1884.6 2002.53  1924.6  2006.1  1968.6 2007.97  2000.3 2008.81  2066.9 2009.13
#Mann= 3 ,-1,0
       0     .05       0   660.4    .045       0  668.86     .05       0
#XS Ineff= 2 , 0
                         1462.69         1998.92
Permanent Ineff=
       F       F
Bank Sta=660.4,668.86
XS Rating Curve= 0 ,0
Exp/Cntr(USF)=0,0
Exp/Cntr=0.3,0.1

Type RM Length L Ch R = 1 ,1527    ,771.6,768.5,766.3
XS GIS Cut Line= 5
 2266868.7368161634488.7698619092267148.14994129634856.805898667
 2267137.2816523635100.096937401  2267545.490607635787.637976707
2268102.95211121635796.643705865
#Sta/Elev= 30
       0 2002.02    70.8 2001.47    85.9 2002.12   136.9 2002.09   514.5 1999.66
   569.7 2000.01   608.1 1999.56   654.6 1997.47   661.41996.174   666.7 1995.12
   671.7 1996.16   674.7 1996.98   698.7 1997.71   796.1 1997.87  1144.2 1996.48
  1301.1  1996.7  1362.3  1996.4  1437.2 1994.13  1469.8  1996.8  1501.9 1998.15
  1647.2 1996.94  1723.9 1999.16  1783.9 1998.99  1875.5 2000.45  1896.7 2000.46
  1911.9 1999.52    1936 2002.12    2004 2006.62    2036 2007.76  2062.7 2007.74
#Mann= 3 ,-1,0
       0     .05       0   661.4    .045       0   671.7     .05       0
#XS Ineff= 2 , 0
                         1512.15         1998.99
Permanent Ineff=
       F       F
Bank Sta=661.4,671.7
XS Rating Curve= 0 ,0
Exp/Cntr(USF)=0,0
Exp/Cntr=0.3,0.1

Type RM Length L Ch R = 1 ,759     ,,,
XS GIS Cut Line= 4
2266709.49827378634616.2092221782266614.46938329635443.204100585
2267193.04670061636211.936402222 2268324.2119697636327.804861984
#Sta/Elev= 30
       0 2001.88   375.4 2001.38   423.7 1998.54   476.1 1997.13   492.2 1994.91
   516.3 1997.04   786.6 1997.65  1021.5 1997.09  1085.2 1995.63 1090.99 1994.26
  1097.9 1992.62  1104.1 1994.26  1110.3 1995.35  1207.8 1997.33  1530.8 1997.29
  1771.1 1995.53  1886.3 1995.78  1950.5  1993.8    1959  1991.7  1980.9 1994.22
  2078.9 1996.56  2360.6 1995.69  2380.7 1992.57  2392.8 1994.73  2457.1 1998.22
  2795.7 1997.97    2807 1997.37    2815 1995.66  2843.2 1999.37  2931.7 2003.87
#Mann= 4 ,-1,0
       0     .06       0      50     .05       0 1090.99    .045       0
  1104.1     .05       0
#XS Ineff= 2 , 0
          621.97 2000.32 2195.12         1999.63
Permanent Ineff=
       F       F
Bank Sta=1090.99,1104.1
XS Rating Curve= 0 ,0
Exp/Cntr(USF)=0,0
Exp/Cntr=0.3,0.1
LCMann Table=0

Chan Stop Cuts=-1
Use User Specified Reach Order=0
Composite Channel Slope=5